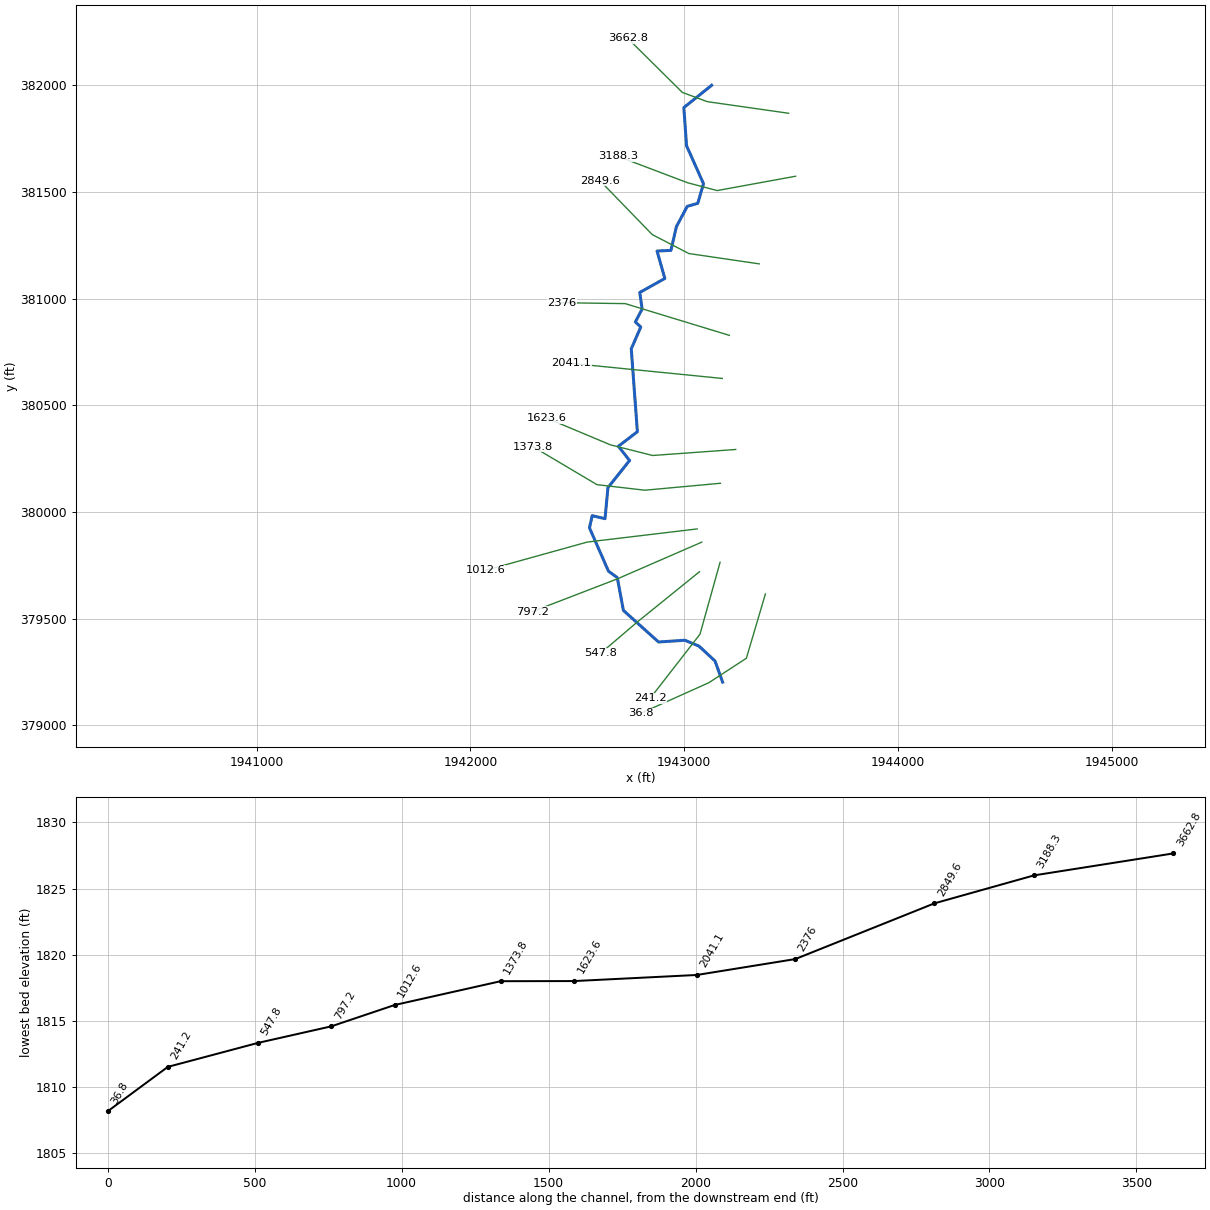
--- LILICKRN.prj (project) ---

Proj Title=LILICKRN
Current Plan=p01
Default Exp/Contr=0,0
English Units
Geom File=g01
Flow File=f01
Plan File=p01
BEGIN DESCRIPTION:
END DESCRIPTION:
DSS Export Rating Curves= 0
DSS Export Rating Curve Sorted= 0
DSS Export Volume Flow Curves= 0
DXF OffsetX= 0
DXF OffsetY= 0
DXF ScaleX= 0
DXF ScaleY= 0

--- LILICKRN.p01 (plan) ---

Plan Title=Floodplain
Program Version=4.00
Geom File=g01
Flow File=f01
K Sum by GR=0
Std Step Tol=0.01
Critical Tol=0.01
Num of Std Step Trials=20
Max Error Tol=0.3
Flow Tol Ratio=0.001
Split Flow NTrial=30
Split Flow Tol=0.02
Split Flow Ratio=0.02
Log Output Level=0
Friction Slope Method=1
Unsteady Friction Slope Method=2
Unsteady Bridges Friction Slope Method=1
Global Log Level=0
CheckData=False
Run HTab=0
Run UNet=0
Run PostProcess=0
UNET Theta=0
UNET Theta Warmup=0
UNET ZTol=0
UNET ZSATol=0
UNET MxIter=0
UNET MaxInSteps=0
UNET DtIC=0
UNET DtMin=0
UNET MaxCRTS=0
UNET WFStab=0
UNET SFStab=0
UNET WFX=0
UNET SFX=0
UNET DSS MLevel=0
UNET DZMax Abort=0
UNET Convert EG Bridges=0
UNET Use Existing IB Tables=0
UNET Froude Limit=0
UNET Froude Power=0
Write IC File=0
Echo Input=False
Echo Output=False
Write Detailed=0

--- LILICKRN.f01 (steady flow) ---

Flow Title=NFF Regression Equation
Program Version=4.00
Number of Profiles=1
Profile Names=P100yr
River Rch & RM=LILICKRN,Main      ,3662.8
517.8802
River Rch & RM=LILICKRN,Main      ,2376
549.5798
River Rch & RM=LILICKRN,Main      ,241.2
590.6300
Boundary for River Rch & Prof#=LILICKRN,Main      ,1
Up Type=0
Dn Type=3
Dn Slope=0.009104

--- LILICKRN.g01 (geometry) ---

Geom Title=USGS 10m DEM
Program Version=4.10

River Reach=LILICKRN        ,Main
Reach XY= 30
     1943128.869      382000.849     1942998.773      381896.139
     1943011.466      381717.179     1943090.792      381539.488
     1943063.821       381447.47     1943014.639      381433.191
      1942963.87      381337.999     1942938.485      381226.943
     1942873.438       381223.77     1942909.928      381095.261
     1942792.525      381029.579     1942803.631      380951.839
       1942771.9      380891.552     1942797.285      380867.754
     1942752.862      380765.581     1942781.419      380376.883
     1942692.574      380308.662     1942744.929      380242.028
      1942643.75      380114.871     1942630.083      379969.355
     1942570.094      379983.425     1942557.402       379926.31
     1942646.248      379723.235     1942687.497      379693.091
     1942716.055      379539.198     1942880.469      379391.217
     1943003.385       379399.55     1943069.546       379371.92
     1943144.734      379302.171     1943180.086      379203.277

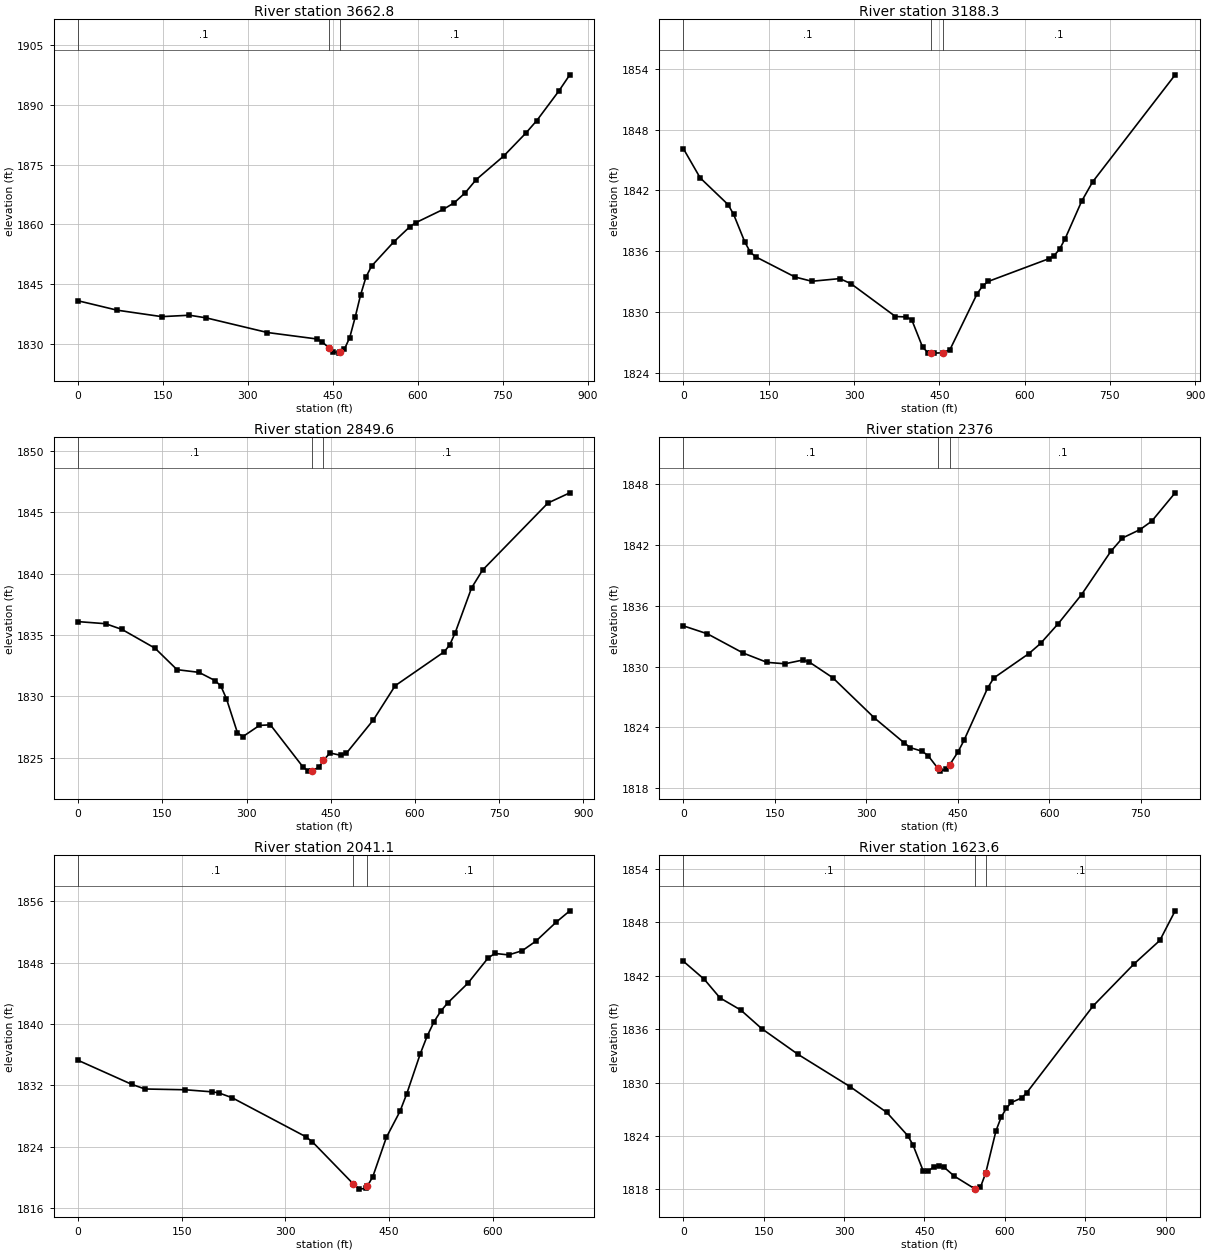
Type RM Length L Ch R = 1 ,3662.8  ,476.3,474.5,471.9
XS GIS Cut Line= 4
     1943488.802      381869.646     1943109.028      381923.899
      1942991.84      381967.302     1942736.329      382220.838
#Sta/Elev= 30
       0 1840.81    68.9 1838.45   147.6 1836.83   196.7 1837.18   226.2 1836.52
   334.4 1832.84   422.1 1831.21   431.7 1830.42   443.4 1828.94   450.9 1828.03
   460.5 1827.66   463.4 1827.94   470.2 1828.59   479.8 1831.56   489.4 1836.66
     499 1842.27   508.6 1846.79   518.3 1849.51   557.2 1855.54   586.4 1859.47
   596.2 1860.41   644.8 1863.76   664.2 1865.41   683.7 1867.92   703.2 1871.25
   751.8 1877.17   790.7  1882.9   810.2 1886.07   849.1 1893.48   868.6 1897.58
#Mann= 3 , 0 , 0
       0      .1       0   443.4    .045       0   463.4      .1       0
Bank Sta=443.4,463.4
XS Rating Curve= 0 ,0
Exp/Cntr=0.3,0.1

Type RM Length L Ch R = 1 ,3188.3  ,342.7,338.6,330.2
XS GIS Cut Line= 4
     1943521.354      381574.507       1943154.6      381507.232
     1943015.712      381544.125     1942690.191      381667.823
#Sta/Elev= 30
       0  1846.1    29.4 1843.24    78.5 1840.61    88.3 1839.64   107.9 1836.93
   117.8 1835.91   127.6 1835.46   196.2 1833.49   225.7 1833.07   274.8 1833.33
   294.4 1832.84   372.9  1829.6     392 1829.56   401.6 1829.27   420.8 1826.56
   430.4 1826.04   435.9 1826.02   439.9    1826   455.9 1826.03   468.7 1826.34
   516.6 1831.85   526.2 1832.61   535.9 1833.05   642.3 1835.28     652  1835.6
   661.7 1836.24   671.4 1837.27   700.4 1840.95   719.7 1842.85   864.8 1853.38
#Mann= 3 , 0 , 0
       0      .1       0   435.9    .045       0   455.9      .1       0
Bank Sta=435.9,455.9
XS Rating Curve= 0 ,0
Exp/Cntr=0.3,0.1

Type RM Length L Ch R = 1 ,2849.6  ,464.4,473.7,461.5
XS GIS Cut Line= 4
     1943351.477      381163.655     1943022.222      381212.093
     1942850.781      381301.069      1942607.44      381552.569
#Sta/Elev= 30
       0 1836.09    48.9 1835.92    78.3 1835.45     137 1833.92   176.2 1832.17
   215.3 1831.95   244.7 1831.26   254.5 1830.81   264.3 1829.79   283.9 1827.01
   293.6 1826.71     323 1827.62   342.5 1827.67   400.4 1824.24   410.1 1823.89
   417.1 1823.93   429.4 1824.22   437.1 1824.78   448.7 1825.37     468 1825.18
   477.7 1825.34     526 1828.07   564.8 1830.86   652.3 1833.63     662 1834.19
   671.8 1835.19   700.9 1838.84   720.4 1840.29     837 1845.77   875.9  1846.6
#Mann= 3 , 0 , 0
       0      .1       0   417.1    .045       0   437.1      .1       0
Bank Sta=417.1,437.1
XS Rating Curve= 0 ,0
Exp/Cntr=0.3,0.1

Type RM Length L Ch R = 1 ,2376    ,311.2,334.8,335.7
XS GIS Cut Line= 3
     1943211.727      380828.612     1942724.913      380977.284
     1942427.604      380981.625
#Sta/Elev= 30
       0 1834.02    39.2 1833.24    97.9 1831.34     137 1830.42   166.4 1830.28
   195.8 1830.65   205.6 1830.48   244.7 1828.91   313.2 1824.93   362.2 1822.46
     372    1822   391.6 1821.64   401.3  1821.2   416.7    1820   420.9 1819.68
   430.7 1819.87   436.7 1820.31   450.3 1821.58   460.1 1822.72   499.2 1827.93
     509 1828.88   566.6 1831.29   585.7 1832.29   614.5 1834.23   652.9 1837.11
   700.8 1841.37     720  1842.7   748.8 1843.53     768 1844.36   806.4 1847.16
#Mann= 3 , 0 , 0
       0      .1       0   416.7    .045       0   436.7      .1       0
Bank Sta=416.7,436.7
XS Rating Curve= 0 ,0
Exp/Cntr=0.3,0.1

Type RM Length L Ch R = 1 ,2041.1  ,409.9,417.6,415.2
XS GIS Cut Line= 3
     1943178.778       380626.62     1942764.364       380668.01
     1942471.007      380697.337
#Sta/Elev= 30
       0 1835.28    77.5 1832.15    96.8 1831.54     155 1831.44   193.7 1831.17
   203.4 1831.04   222.8  1830.4   329.3 1825.32     339 1824.64   398.2 1819.15
   406.8 1818.48   416.5 1818.58   418.2 1818.84   426.3  1820.1     446 1825.24
   465.6 1828.62   475.4 1830.91   495.1 1836.16   504.9 1838.43   514.8  1840.3
   524.6 1841.69   534.4 1842.74   563.9 1845.34   593.4 1848.66   603.2 1849.22
   622.8 1849.03   642.5 1849.58   662.2 1850.82   691.6  1853.3   711.3 1854.78
#Mann= 3 , 0 , 0
       0      .1       0   398.2    .045       0   418.2      .1       0
Bank Sta=398.2,418.2
XS Rating Curve= 0 ,0
Exp/Cntr=0.3,0.1

Type RM Length L Ch R = 1 ,1623.6  ,239.1,249.7,252
XS GIS Cut Line= 4
     1943241.406      380293.691     1942852.951      380265.479
     1942655.469      380315.392     1942355.989       380441.26
#Sta/Elev= 30
       0 1843.63      39  1841.6    68.2 1839.52   107.1 1838.15     146 1836.07
   214.2 1833.16   311.6 1829.52   379.7 1826.64   418.6 1824.04   428.3 1823.02
   447.7 1820.05   457.4 1820.08   467.1  1820.5   476.8 1820.62   486.5 1820.48
   505.9 1819.47   544.3 1818.04   544.7 1818.02   554.4 1818.22   564.3 1819.83
   583.5 1824.58   593.2 1826.11   602.7 1827.11   612.3 1827.76   631.4 1828.27
   640.9 1828.86   765.2 1838.64   841.6 1843.36   889.4 1845.98     918 1849.31
#Mann= 3 , 0 , 0
       0      .1       0   544.3    .045       0   564.3      .1       0
Bank Sta=544.3,564.3
XS Rating Curve= 0 ,0
Exp/Cntr=0.3,0.1

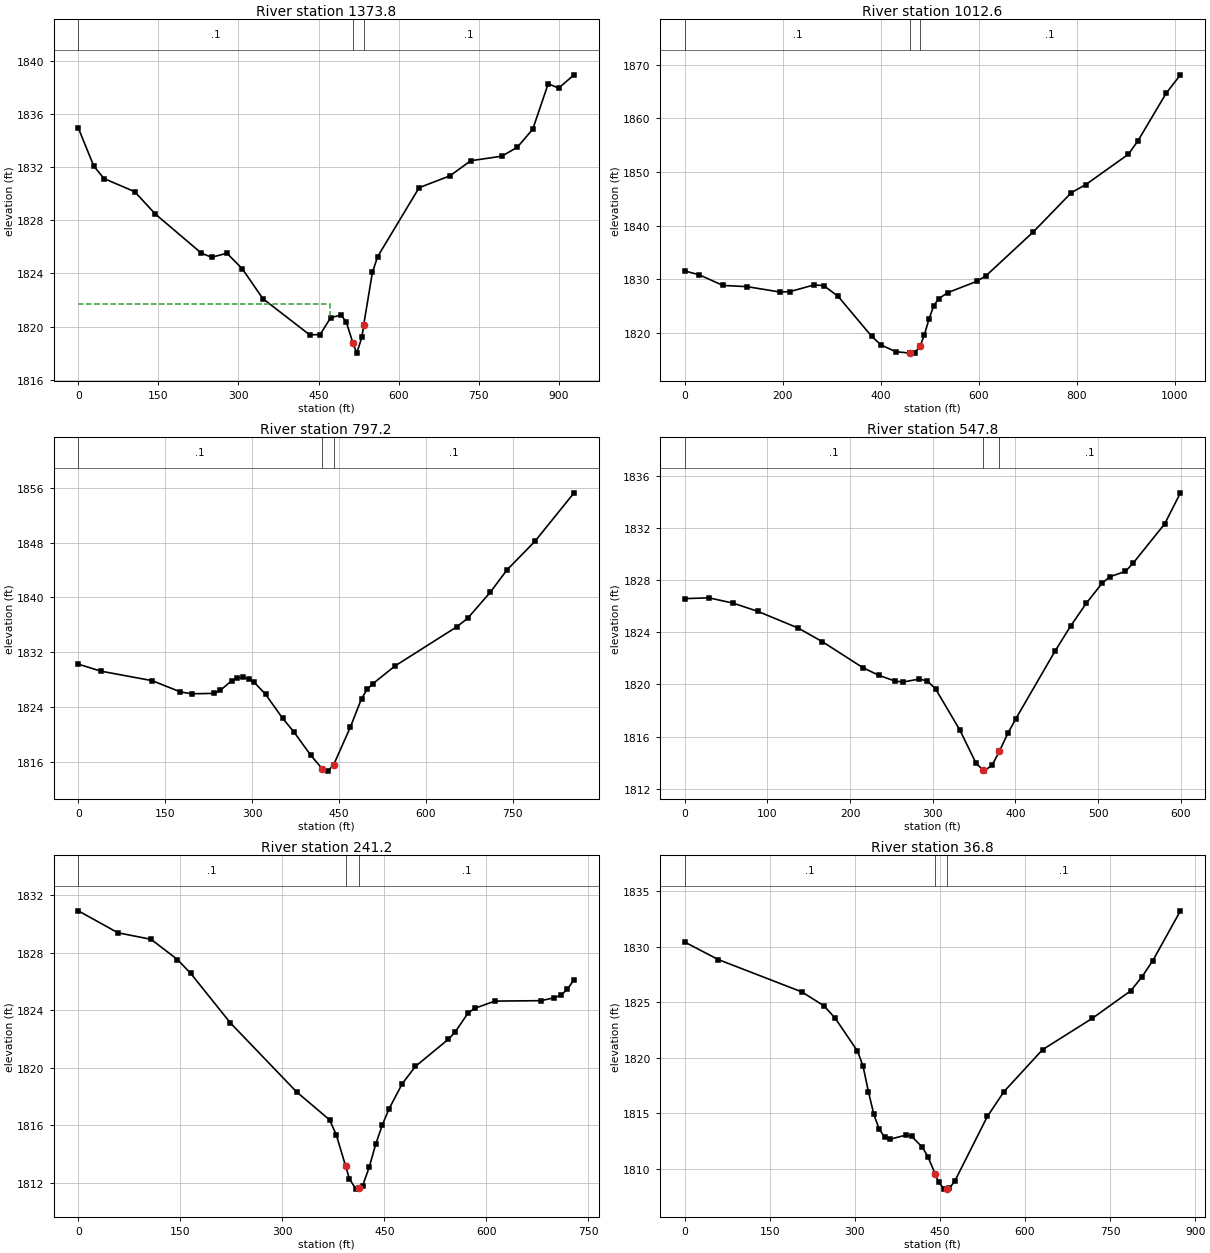
Type RM Length L Ch R = 1 ,1373.8  ,344.5,361.2,331.6
XS GIS Cut Line= 4
     1943169.791      380135.271     1942816.059      380102.718
     1942592.535       380128.76     1942293.055      380306.712
#Sta/Elev= 30
       0 1834.94    28.8 1832.09      48 1831.14   105.6 1830.15     144 1828.48
   230.4 1825.53   249.6 1825.22   278.4 1825.52   307.2 1824.35   345.6 1822.11
   433.5 1819.38   453.1 1819.41   472.6 1820.68   492.2 1820.87     502 1820.34
   514.6 1818.74   521.6 1818.01   531.3 1819.24   534.6 1820.14   550.9  1824.1
   560.7 1825.27   638.3 1830.45   696.4 1831.35   735.1 1832.48   793.2 1832.82
   822.2 1833.49   851.2 1834.85   880.2 1838.27   899.6 1837.94   928.6 1838.94
#Mann= 3 , 0 , 0
       0      .1       0   514.6    .045       0   534.6      .1       0
#XS Ineff= 2 , 0
           471.2 1821.69
Permanent Ineff=
       F       F
Bank Sta=514.6,534.6
XS Rating Curve= 0 ,0
Exp/Cntr=0.3,0.1

Type RM Length L Ch R = 1 ,1012.6  ,205.5,215.4,224.6
XS GIS Cut Line= 3
     1943061.179      379921.316     1942546.962      379859.663
     1942071.701      379727.284
#Sta/Elev= 30
       0 1831.55    29.3 1830.84    78.2 1828.84     127 1828.62   195.4  1827.6
     215  1827.7   263.8 1828.94   283.4 1828.82   312.7 1826.83   381.1 1819.37
   400.6 1817.74     430 1816.49   459.3 1816.21   459.8 1816.22     469 1816.32
   479.8 1817.45   488.6 1819.53   498.4  1822.6   508.1 1825.05   517.9 1826.38
   537.2 1827.52   595.3 1829.59   614.6 1830.65   711.4 1838.86   788.8 1846.17
   817.8 1847.64   904.8 1853.31   924.2 1855.78   982.2 1864.73  1011.2 1868.15
#Mann= 3 , 0 , 0
       0      .1       0   459.8    .045       0   479.8      .1       0
Bank Sta=459.8,479.8
XS Rating Curve= 0 ,0
Exp/Cntr=0.3,0.1

Type RM Length L Ch R = 1 ,797.2   ,240.9,249.4,258.9
XS GIS Cut Line= 3
     1943082.639       379859.32     1942687.497      379687.126
     1942291.065      379533.924
#Sta/Elev= 30
       0 1830.23    39.2  1829.2   127.4 1827.82   176.3 1826.17   195.9  1825.9
   235.1 1825.96   244.9 1826.38   264.5 1827.79   274.3 1828.22   284.1  1828.3
   293.9 1828.08   303.7 1827.58   323.3 1825.82   352.7 1822.33   372.2 1820.33
   401.6 1816.89     421 1814.96     431  1814.6     441 1815.56   469.7 1821.02
     489 1825.19   498.6 1826.54   508.3 1827.35   546.9 1829.97   653.2 1835.67
   672.5 1836.95   711.2 1840.72   740.1 1843.99   788.4 1848.17     856 1855.26
#Mann= 3 , 0 , 0
       0      .1       0     421    .045       0     441      .1       0
Bank Sta=421,441
XS Rating Curve= 0 ,0
Exp/Cntr=0.3,0.1

Type RM Length L Ch R = 1 ,547.8   ,300.6,306.6,311.5
XS GIS Cut Line= 3
     1943072.135      379720.774     1942783.101      379486.657
     1942609.896       379338.83
#Sta/Elev= 30
       0 1826.59    29.4 1826.65    58.7 1826.24    88.1 1825.62     137 1824.34
   166.4 1823.29   215.3  1821.3   234.9  1820.7   254.5 1820.26   264.3 1820.19
   283.9 1820.42   293.6 1820.26   303.4 1819.67   332.8 1816.51   352.4 1813.96
   360.6 1813.45   362.2 1813.35     372 1813.82   380.6 1814.86   390.9 1816.25
   400.4 1817.35   447.9 1822.55   466.8 1824.48   485.8 1826.23   504.8 1827.76
   514.3 1828.27   533.2 1828.68   542.7 1829.33   580.7 1832.33   599.7 1834.71
#Mann= 3 , 0 , 0
       0      .1       0   360.6    .045       0   380.6      .1       0
Bank Sta=360.6,380.6
XS Rating Curve= 0 ,0
Exp/Cntr=0.3,0.1

Type RM Length L Ch R = 1 ,241.2   ,213.2,204.4,196.4
XS GIS Cut Line= 3
     1943168.294      379764.863     1943074.305      379427.805
       1942842.1      379128.326
#Sta/Elev= 30
       0  1830.9    58.3 1829.37   106.9 1828.92   145.8 1827.51   165.2 1826.55
   223.6  1823.1   320.8 1818.31   369.4 1816.36   379.1 1815.34     393 1813.15
   398.5 1812.26   408.2 1811.54     413 1811.65   417.9 1811.76   427.6 1813.05
   437.4 1814.69   447.1 1816.02   456.8 1817.12   476.2 1818.87   495.7 1820.08
   544.2 1821.97     554 1822.47   573.4 1823.81   583.1 1824.12   612.3 1824.62
   680.3 1824.65   699.7 1824.85   709.4 1825.03   719.2 1825.45   728.9 1826.12
#Mann= 3 , 0 , 0
       0      .1       0     393    .045       0     413      .1       0
Bank Sta=393,413
XS Rating Curve= 0 ,0
Exp/Cntr=0.3,0.1

Type RM Length L Ch R = 1 ,36.8    ,48.8,36.8,24.1
XS GIS Cut Line= 4
     1943380.295      379616.607     1943291.273      379315.056
     1943115.782      379200.558     1942796.528      379056.712
#Sta/Elev= 30
       0 1830.42      59 1828.85   206.3 1825.94   245.6 1824.68   265.3 1823.57
   304.6 1820.62   314.4 1819.28   323.9 1816.96   333.5 1814.92     343 1813.57
   352.5 1812.89     362 1812.68   390.6 1813.06   400.1 1812.94   419.2 1811.95
   428.7 1811.12   442.1 1809.51   447.8 1808.82   457.3 1808.19   462.1 1808.24
   466.8 1808.28   476.3 1808.92   533.7 1814.73   562.9 1816.96     631 1820.74
   718.5 1823.55   786.6 1826.04     806 1827.27   825.5 1828.76   874.1 1833.23
#Mann= 3 , 0 , 0
       0      .1       0   442.1    .045       0   462.1      .1       0
Bank Sta=442.1,462.1
XS Rating Curve= 0 ,0
Exp/Cntr=0.3,0.1

Chan Stop Cuts=-1
Use User Specified Reach Order=0
Composite Channel Slope=5